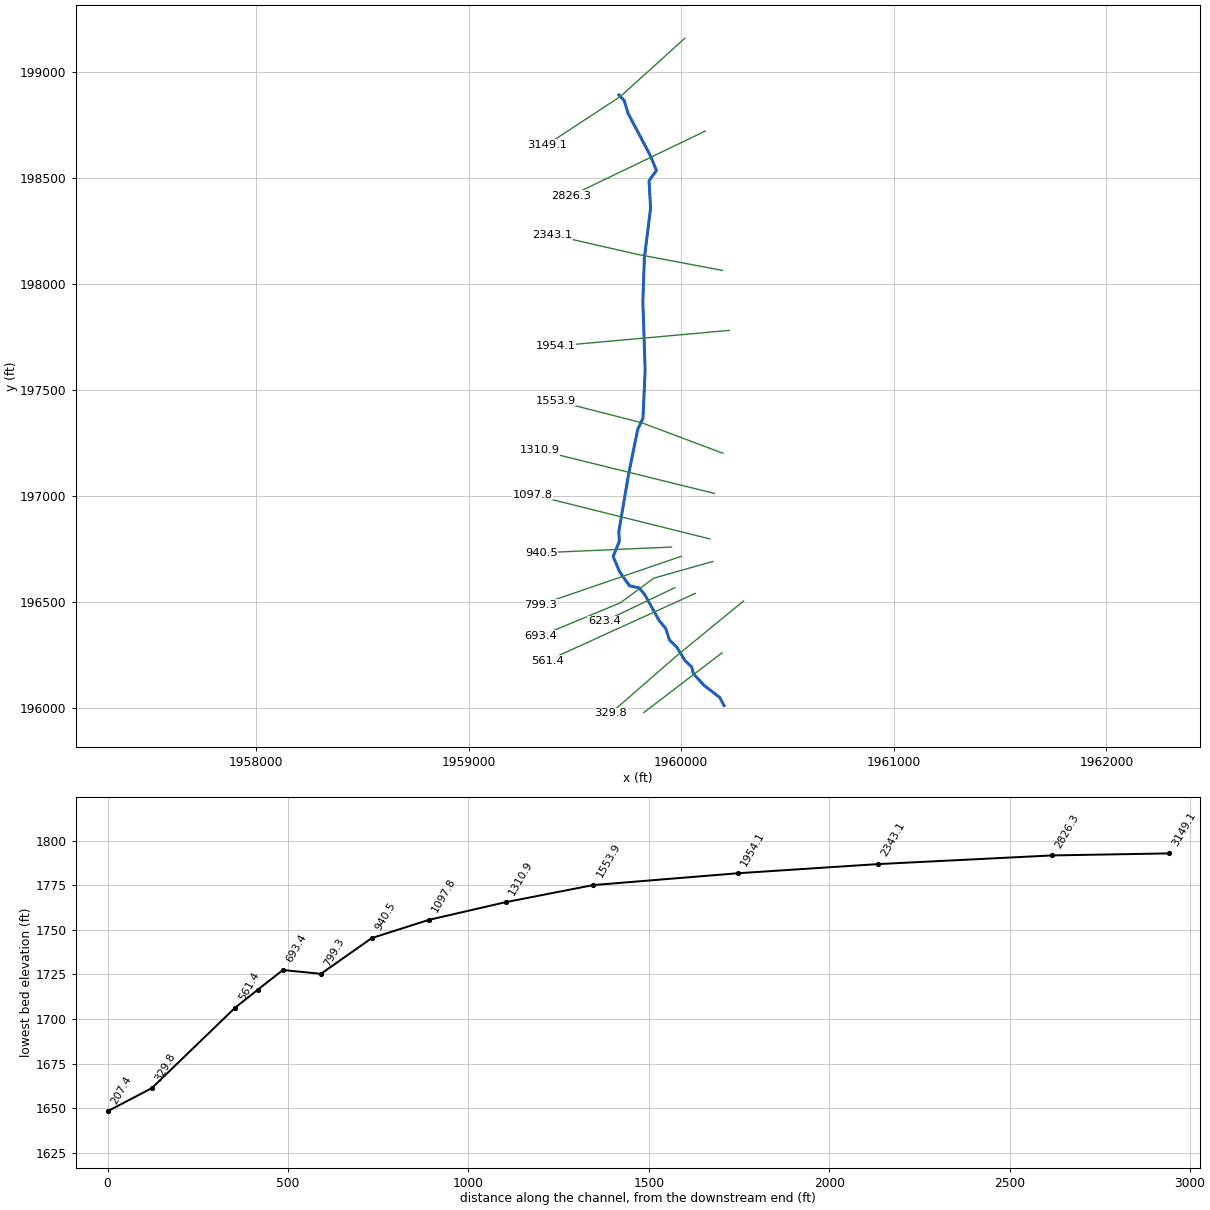
--- DstlckCrk.prj (project) ---

Proj Title=DstlckCrk
Current Plan=p01
Default Exp/Contr=0,0
English Units
Geom File=g01
Flow File=f01
Plan File=p01
BEGIN DESCRIPTION:
END DESCRIPTION:
DSS Export Rating Curves= 0
DSS Export Rating Curve Sorted= 0
DSS Export Volume Flow Curves= 0
DXF OffsetX= 0
DXF OffsetY= 0
DXF ScaleX= 0
DXF ScaleY= 0

--- DstlckCrk.p01 (plan) ---

Plan Title=Floodplain
Program Version=4.00
Geom File=g01
Flow File=f01
K Sum by GR=0
Std Step Tol=0.01
Critical Tol=0.01
Num of Std Step Trials=20
Max Error Tol=0.3
Flow Tol Ratio=0.001
Split Flow NTrial=30
Split Flow Tol=0.02
Split Flow Ratio=0.02
Log Output Level=0
Friction Slope Method=1
Unsteady Friction Slope Method=2
Unsteady Bridges Friction Slope Method=1
Global Log Level=0
CheckData=False
Run HTab=0
Run UNet=0
Run PostProcess=0
UNET Theta=0
UNET Theta Warmup=0
UNET ZTol=0
UNET ZSATol=0
UNET MxIter=0
UNET MaxInSteps=0
UNET DtIC=0
UNET DtMin=0
UNET MaxCRTS=0
UNET WFStab=0
UNET SFStab=0
UNET WFX=0
UNET SFX=0
UNET DSS MLevel=0
UNET DZMax Abort=0
UNET Convert EG Bridges=0
UNET Use Existing IB Tables=0
UNET Froude Limit=0
UNET Froude Power=0
Write IC File=0
Echo Input=False
Echo Output=False
Write Detailed=0

--- DstlckCrk.f01 (steady flow) ---

Flow Title=NFF Regression Equation
Program Version=4.00
Number of Profiles=1
Profile Names=P100yr
River Rch & RM=DstlckCrk,Main      ,3149.1
464.7152
River Rch & RM=DstlckCrk,Main      ,2343.1
485.8406
River Rch & RM=DstlckCrk,Main      ,329.8
537.6899
Boundary for River Rch & Prof#=DstlckCrk,Main      ,1
Up Type=0
Dn Type=3
Dn Slope=0.154572

--- DstlckCrk.g01 (geometry) ---

Geom Title=USGS 3m DEM
Program Version=4.10

River Reach=DstlckCrk       ,Main
Reach XY= 30
     1959707.333      198890.372     1959732.073      198863.028
     1959750.302      198803.133     1959854.469      198605.216
     1959883.434      198534.757     1959848.678       198486.26
     1959855.952      198356.936     1959826.854      198124.152
      1959819.58      197917.233     1959830.334       197592.47
     1959820.152      197366.398     1959795.113       197313.34
     1959751.789       197099.36     1959706.423      196832.202
     1959709.288      196787.345      1959679.93      196716.104
     1959709.788      196644.424      1959756.75      196577.786
     1959802.315      196567.565     1959829.384      196534.642
     1959896.202       196413.94     1959927.455       196376.22
     1959944.957      196322.087     1959978.107      196290.004
     1960017.982      196225.341     1960049.236      196195.166
     1960057.857      196162.834     1960108.006      196108.191
      1960181.44      196051.635     1960201.435      196013.614

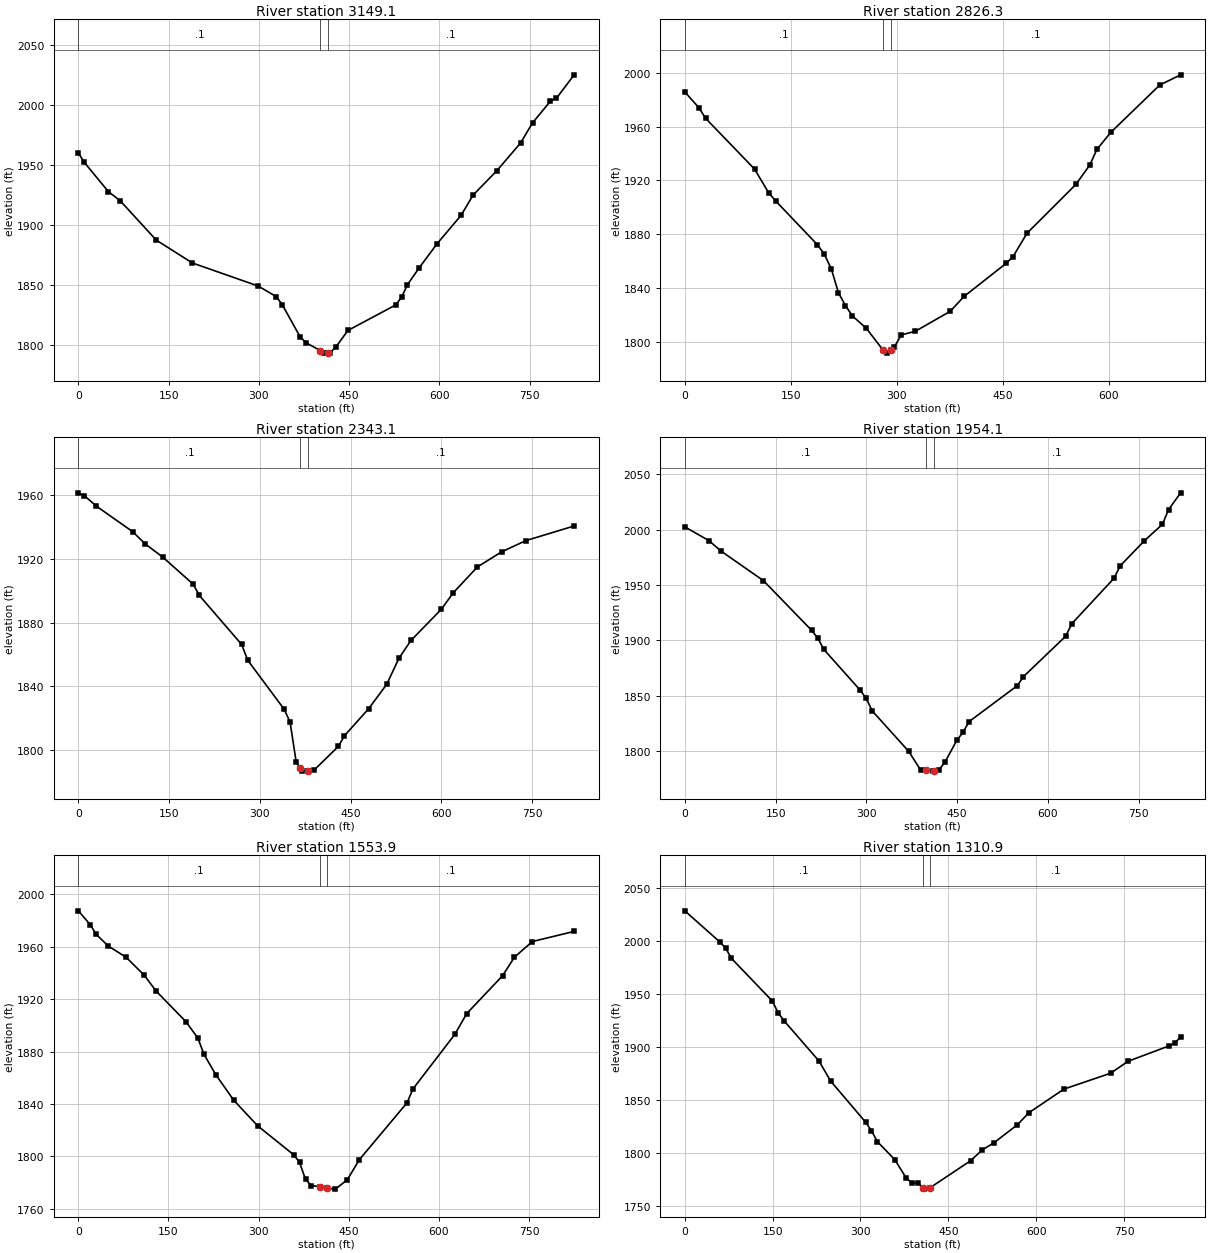
Type RM Length L Ch R = 1 ,3149.1  ,328.7,322.8,319.8
XS GIS Cut Line= 3
     1960016.916      199156.987     1959714.043      198882.957
     1959366.719      198654.921
#Sta/Elev= 30
       0 1959.71      10 1951.75    49.8 1927.52    69.7 1919.74   129.5 1887.02
   189.3    1868   298.9 1848.73   328.8 1839.96   338.7 1833.33   368.6 1806.36
   378.6 1801.38   402.4 1794.91   408.4 1792.82   414.4 1792.96   418.3 1793.05
   428.2  1798.1     448 1811.73   527.2 1832.93     537 1839.32   546.9 1849.86
   566.7 1864.12   596.4 1884.18     636 1907.66   655.8 1924.44   695.3 1944.79
   734.9 1967.99   754.7 1984.74   784.4 2002.76   794.3 2005.14   823.9 2024.78
#Mann= 3 , 0 , 0
       0      .1       0   402.4    .045       0   414.4      .1       0
Bank Sta=402.4,414.4
XS Rating Curve= 0 ,0
Exp/Cntr=0.3,0.1

Type RM Length L Ch R = 1 ,2826.3  ,497.3,483.1,469.1
XS GIS Cut Line= 2
     1960113.599      198720.167     1959481.345      198415.536
#Sta/Elev= 30
       0 1985.84    19.8 1974.21    29.6 1966.13    98.8 1928.45   118.6 1910.94
   128.5 1904.88   187.8  1872.2   197.7 1865.05   207.6 1853.93   217.5 1836.51
   227.4 1827.03   237.2 1819.36     257  1810.1   280.1 1794.31   286.7 1791.69
   292.1 1794.15   296.5 1796.16   306.4 1805.22   326.2 1807.89   375.6 1822.73
   395.4  1833.9   454.7 1858.35   464.6 1863.42   484.4 1880.83   553.5 1917.06
   573.3 1931.55   583.2 1943.05     603 1955.78   672.2 1990.93   701.8 1998.54
#Mann= 3 , 0 , 0
       0      .1       0   280.1    .045       0   292.1      .1       0
Bank Sta=280.1,292.1
XS Rating Curve= 0 ,0
Exp/Cntr=0.3,0.1

Type RM Length L Ch R = 1 ,2343.1  ,383,388.9,394.7
XS GIS Cut Line= 3
     1960193.805       198063.69     1959791.071      198139.809
     1959391.959      198231.172
#Sta/Elev= 30
       0 1961.54      10 1959.73      30 1953.12      90 1937.09     110 1929.62
     140 1921.01   189.9 1904.13   199.9 1897.14   269.9 1866.33   279.9 1856.45
   339.9 1825.76   349.9 1817.66   359.9 1792.73   366.7 1788.82   369.9 1786.98
   378.7 1786.85   379.9 1786.83   389.9 1787.62   429.8 1802.39   439.8  1809.1
   479.8 1826.04   509.7 1841.41   529.7 1857.65   549.7 1868.89   599.6 1888.34
   619.6 1898.82   659.5 1915.05   699.5  1924.5   739.4 1931.53   819.3 1940.73
#Mann= 3 , 0 , 0
       0      .1       0   366.7    .045       0   378.7      .1       0
Bank Sta=366.7,378.7
XS Rating Curve= 0 ,0
Exp/Cntr=0.3,0.1

Type RM Length L Ch R = 1 ,1954.1  ,409.8,400.3,393.2
XS GIS Cut Line= 3
     1960225.729      197780.949     1959817.892      197744.083
     1959410.055      197707.217
#Sta/Elev= 30
       0 2002.44      40  1989.9    59.9 1980.49   129.8 1953.84   209.7 1908.78
   219.7 1901.85   229.7  1891.6   289.6 1854.92   299.6 1847.48   309.6 1836.11
   369.6 1799.71   389.5 1782.74     399 1782.45   409.5 1781.69     411 1781.85
   419.5 1782.74   429.5 1789.54   449.4 1809.62   459.4  1816.6   469.4 1826.36
   549.3 1858.95   559.3 1867.02   629.2 1903.62   639.2 1914.87   709.1 1956.01
   719.1 1967.11   759.1 1989.84     789 2004.73     799  2017.9     819 2033.15
#Mann= 3 , 0 , 0
       0      .1       0     399    .045       0     411      .1       0
Bank Sta=399,411
XS Rating Curve= 0 ,0
Exp/Cntr=0.3,0.1

Type RM Length L Ch R = 1 ,1553.9  ,240.4,242.9,243
XS GIS Cut Line= 3
     1960195.744      197202.299     1959813.947      197345.997
     1959409.748      197449.452
#Sta/Elev= 30
       0 1987.34    19.9 1976.77    29.8 1969.32    49.8 1960.53    79.6 1951.86
   109.4 1938.38   129.4 1926.18   179.1 1902.78     199 1890.23     209    1878
   228.8 1862.33   258.7 1842.83   298.5 1823.32   358.2 1801.35   368.1 1795.58
   378.1 1782.46     388 1777.73   401.9 1777.06   413.9 1775.71   427.8 1775.07
   447.7 1782.25   467.6  1797.5     547 1840.89     557 1851.55   626.5 1893.04
   646.4 1908.98     706  1937.8   725.8 1951.97   755.6 1963.91   825.2 1971.65
#Mann= 3 , 0 , 0
       0      .1       0   401.9    .045       0   413.9      .1       0
Bank Sta=401.9,413.9
XS Rating Curve= 0 ,0
Exp/Cntr=0.3,0.1

Type RM Length L Ch R = 1 ,1310.9  ,213.1,213,213
XS GIS Cut Line= 2
     1960155.749      197013.083      1959333.82      197216.171
#Sta/Elev= 30
       0 2028.37    59.8 1998.97    69.7 1993.18    79.7 1983.41   149.4 1943.21
   159.4 1932.05   169.3  1924.6   229.1 1886.53     249 1867.57   308.8 1828.68
   318.7 1820.74   328.7 1810.44   358.6 1793.31   378.5 1775.55   388.5 1771.42
   398.4 1771.27   407.1 1766.23   408.4 1765.48   419.1 1766.91   488.1 1792.35
     508 1802.57   527.9 1809.28   567.8 1826.24   587.7 1837.71   647.4 1859.97
   727.1 1874.97     757 1886.28   826.7 1900.73   836.7 1903.57   846.6  1909.1
#Mann= 3 , 0 , 0
       0      .1       0   407.1    .045       0   419.1      .1       0
Bank Sta=407.1,419.1
XS Rating Curve= 0 ,0
Exp/Cntr=0.3,0.1

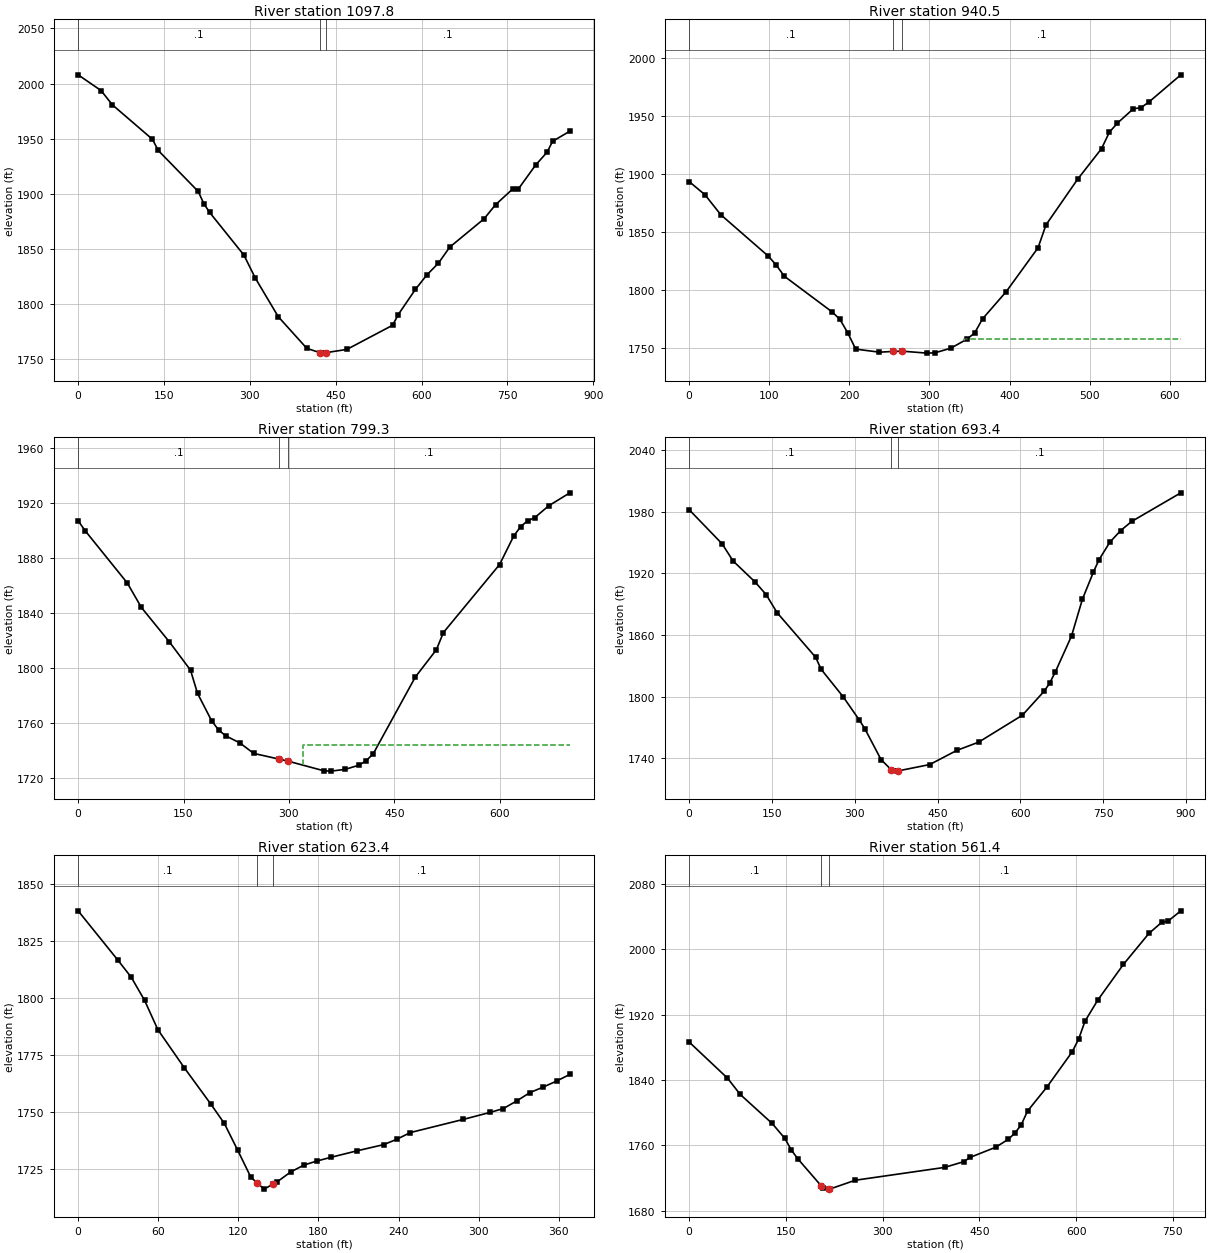
Type RM Length L Ch R = 1 ,1097.8  ,151.3,157.8,164.4
XS GIS Cut Line= 2
     1960134.674        196798.5     1959301.091      197006.577
#Sta/Elev= 30
       0 2007.87      40 1993.64    59.9 1980.65   129.9  1949.4   139.9 1939.34
   209.8 1902.16   219.8 1890.92   229.8 1883.12   289.7 1844.42   309.7 1823.47
   349.7 1788.58   399.6 1759.86   421.8 1756.11   429.6 1755.55   433.8 1756.03
   469.5  1758.9   549.5 1780.82   559.4 1790.55   589.4 1813.37   609.4  1826.5
   629.4 1837.02   649.4 1851.68   709.3 1877.32   729.3 1890.07   759.3 1904.36
   769.2 1904.36   799.2 1925.94   819.2  1937.6   829.2 1947.67   859.2 1956.75
#Mann= 3 , 0 , 0
       0      .1       0   421.8    .045       0   433.8      .1       0
Bank Sta=421.8,433.8
XS Rating Curve= 0 ,0
Exp/Cntr=0.3,0.1

Type RM Length L Ch R = 1 ,940.5   ,134.9,140.9,147
XS GIS Cut Line= 2
     1959954.577      196760.182     1959341.483      196733.359
#Sta/Elev= 30
       0 1893.35    19.8 1881.94    39.6 1864.69      99 1828.93   108.9 1821.18
   118.8 1811.72   178.2 1781.06   188.1 1774.63     198 1762.89   207.9 1748.84
   237.6  1746.2   254.3 1746.83   266.3 1747.05   296.9 1745.38   306.8 1745.64
   326.6 1749.64   346.4 1757.27   356.3 1762.67   366.2 1774.91   395.9 1798.51
   435.5 1836.23   445.4 1855.96     485 1895.42   514.7 1921.68   524.6 1935.94
   534.5 1943.67   554.3 1956.01   564.2 1957.12   574.1 1962.04   613.7 1985.36
#Mann= 3 , 0 , 0
       0      .1       0   254.3    .045       0   266.3      .1       0
#XS Ineff= 2 , 0
                          343.35         1757.61
Permanent Ineff=
       F       F
Bank Sta=254.3,266.3
XS Rating Curve= 0 ,0
Exp/Cntr=0.3,0.1

Type RM Length L Ch R = 1 ,799.3   ,98.1,105.6,112.8
XS GIS Cut Line= 2
     1960000.739      196716.775     1959339.028      196489.379
#Sta/Elev= 30
       0 1907.43      10 1900.18      70 1862.15      90 1844.38   129.9 1819.29
   159.9 1798.79   169.9 1781.88   189.9 1762.02   199.9 1755.23   209.9 1751.04
   229.9 1745.92   249.9 1738.22   286.1 1734.06   298.1 1732.68   349.8 1725.57
   359.8 1725.34   379.8  1726.6   399.8  1729.7   409.8 1732.91   419.8 1737.85
   479.8 1793.77   509.8 1813.66   519.8 1826.16   599.7 1875.59   619.7  1896.2
   629.7 1903.24   639.7 1907.42   649.7 1909.68   669.7 1918.35   699.7 1927.75
#Mann= 3 , 0 , 0
       0      .1       0   286.1    .045       0   298.1      .1       0
#XS Ineff= 2 , 0
                           319.3         1744.54
Permanent Ineff=
       F       F
Bank Sta=286.1,298.1
XS Rating Curve= 0 ,0
Exp/Cntr=0.3,0.1

Type RM Length L Ch R = 1 ,693.4   ,74.2,70,66.1
XS GIS Cut Line= 4
     1960149.445        196692.6     1959871.479      196613.673
     1959713.756      196497.614     1959339.028      196341.733
#Sta/Elev= 30
       0 1982.13    59.8 1948.84    79.7 1932.12   119.6 1911.62   139.5 1899.41
   159.4 1881.77   229.2 1838.34   239.1 1826.67     279 1799.88   308.5 1777.04
   318.3 1768.74   347.7 1738.62   366.2 1728.77   377.1 1727.45   378.2 1727.64
   435.8 1733.85   484.8 1747.62   524.4 1755.67   603.6  1781.9   643.2 1805.38
   653.1  1813.2     663 1823.72   692.6 1859.03   712.4 1894.97   732.2  1921.2
   742.2 1933.16     762  1950.4   781.7 1961.79   801.5 1970.61   890.6 1998.52
#Mann= 3 , 0 , 0
       0      .1       0   366.2    .045       0   378.2      .1       0
Bank Sta=366.2,378.2
XS Rating Curve= 0 ,0
Exp/Cntr=0.3,0.1

Type RM Length L Ch R = 1 ,623.4   ,62.3,61.9,61.5
XS GIS Cut Line= 2
     1959970.675      196569.035     1959638.367      196410.321
#Sta/Elev= 30
       0 1838.29    29.9 1816.59    39.8 1809.18    49.8 1799.03    59.7 1786.24
    79.6 1769.47    99.5 1753.53   109.5 1745.17   119.4 1733.54   129.4 1721.55
   134.2 1719.04   139.3 1716.37   146.2 1718.63   149.3 1719.65   159.2 1723.89
   169.2 1726.93   179.2 1728.74   189.1 1730.27     209 1733.17   228.9 1735.87
   238.9 1738.27   248.8 1741.15   288.6 1746.93   308.6 1749.99   318.5 1751.66
   328.4 1754.97   338.4 1758.66   348.4 1761.09   358.3  1763.7   368.3 1766.62
#Mann= 3 , 0 , 0
       0      .1       0   134.2    .045       0   146.2      .1       0
Bank Sta=134.2,146.2
XS Rating Curve= 0 ,0
Exp/Cntr=0.3,0.1

Type RM Length L Ch R = 1 ,561.4   ,226,231.5,237.1
XS GIS Cut Line= 2
     1960065.701      196541.767     1959372.138      196225.641
#Sta/Elev= 30
       0 1886.52    59.4 1842.36    79.2 1822.35   128.7 1786.84   148.5 1768.47
   158.4 1754.32   168.3  1743.7   204.4 1710.79   207.9 1707.95   216.4 1706.64
   217.8 1706.42   257.4 1717.28     396 1733.01   425.6    1740   435.6 1745.28
   475.1 1757.64   494.9 1767.48   504.8 1774.91   514.7 1784.92   524.6 1801.99
   554.3 1831.05   593.9 1874.58   603.8 1890.11   613.7 1912.04   633.5 1937.86
   673.1 1981.41   712.7 2019.39   732.5 2032.94   742.4 2034.47   762.2 2047.09
#Mann= 3 , 0 , 0
       0      .1       0   204.4    .045       0   216.4      .1       0
Bank Sta=204.4,216.4
XS Rating Curve= 0 ,0
Exp/Cntr=0.3,0.1

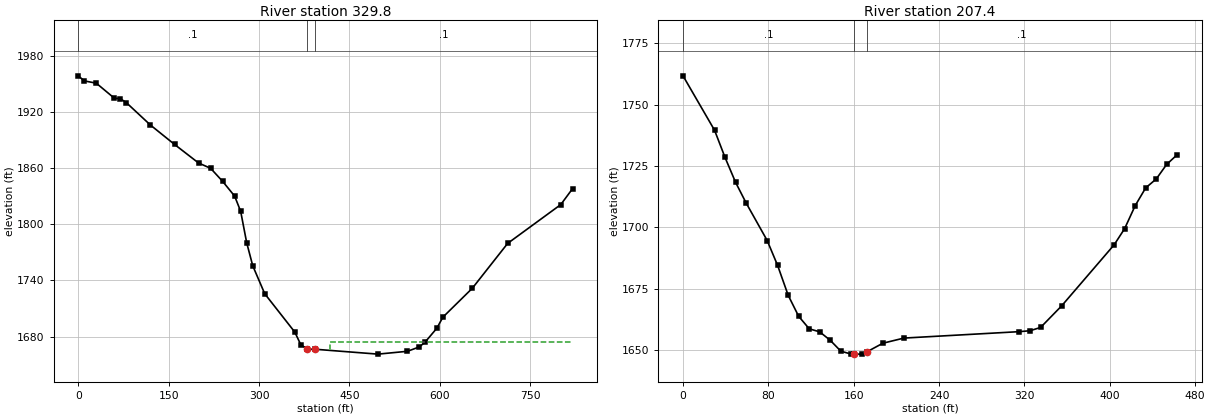
Type RM Length L Ch R = 1 ,329.8   ,123.1,122.4,121.7
XS GIS Cut Line= 3
     1960293.749      196506.284     1959977.406      196246.668
     1959667.734      195976.615
#Sta/Elev= 30
       0 1958.43      10 1953.01    29.9 1950.59    59.9 1934.52    69.9 1934.01
    79.8 1929.79   119.8 1905.85   159.7 1885.21   199.6 1865.36   219.6 1859.68
   239.6 1845.71   259.5 1829.96   269.5 1813.68   279.5 1780.12   289.5 1755.65
   309.4 1725.74   359.3 1684.77   369.3 1671.26   380.1 1666.58   392.1  1666.5
   497.3 1661.25   546.2 1664.28   565.8 1668.92   575.5 1674.08   595.1    1689
   604.9 1700.64   653.8 1731.56   712.5 1779.51   800.6 1820.94   820.1 1837.88
#Mann= 3 , 0 , 0
       0      .1       0   380.1    .045       0   392.1      .1       0
#XS Ineff= 2 , 0
                          417.21         1674.33
Permanent Ineff=
       F       F
Bank Sta=380.1,392.1
XS Rating Curve= 0 ,0
Exp/Cntr=0.3,0.1

Type RM Length L Ch R = 1 ,207.4   ,211,207.4,203.9
XS GIS Cut Line= 2
     1960192.151      196262.043     1959824.295      195980.403
#Sta/Elev= 30
       0 1761.79    29.6 1739.58    39.4  1728.5    49.3 1718.35    59.1    1710
    78.9 1694.64    88.7 1684.46    98.6 1672.29   108.4 1663.75   118.3 1658.64
   128.1 1657.41     138 1653.96   147.9 1649.54   157.7 1648.32   160.5 1648.32
   167.6 1648.33   172.5 1649.28   187.3 1652.76     207 1654.86   315.4 1657.49
   325.3 1657.86   335.2 1659.21   354.9 1667.99   404.2 1692.94     414 1699.52
   423.9  1708.9   433.7 1716.11   443.6 1719.74   453.4  1725.7   463.3 1729.67
#Mann= 3 , 0 , 0
       0      .1       0   160.5    .045       0   172.5      .1       0
Bank Sta=160.5,172.5
XS Rating Curve= 0 ,0
Exp/Cntr=0.3,0.1

Chan Stop Cuts=-1
Use User Specified Reach Order=0
Composite Channel Slope=5